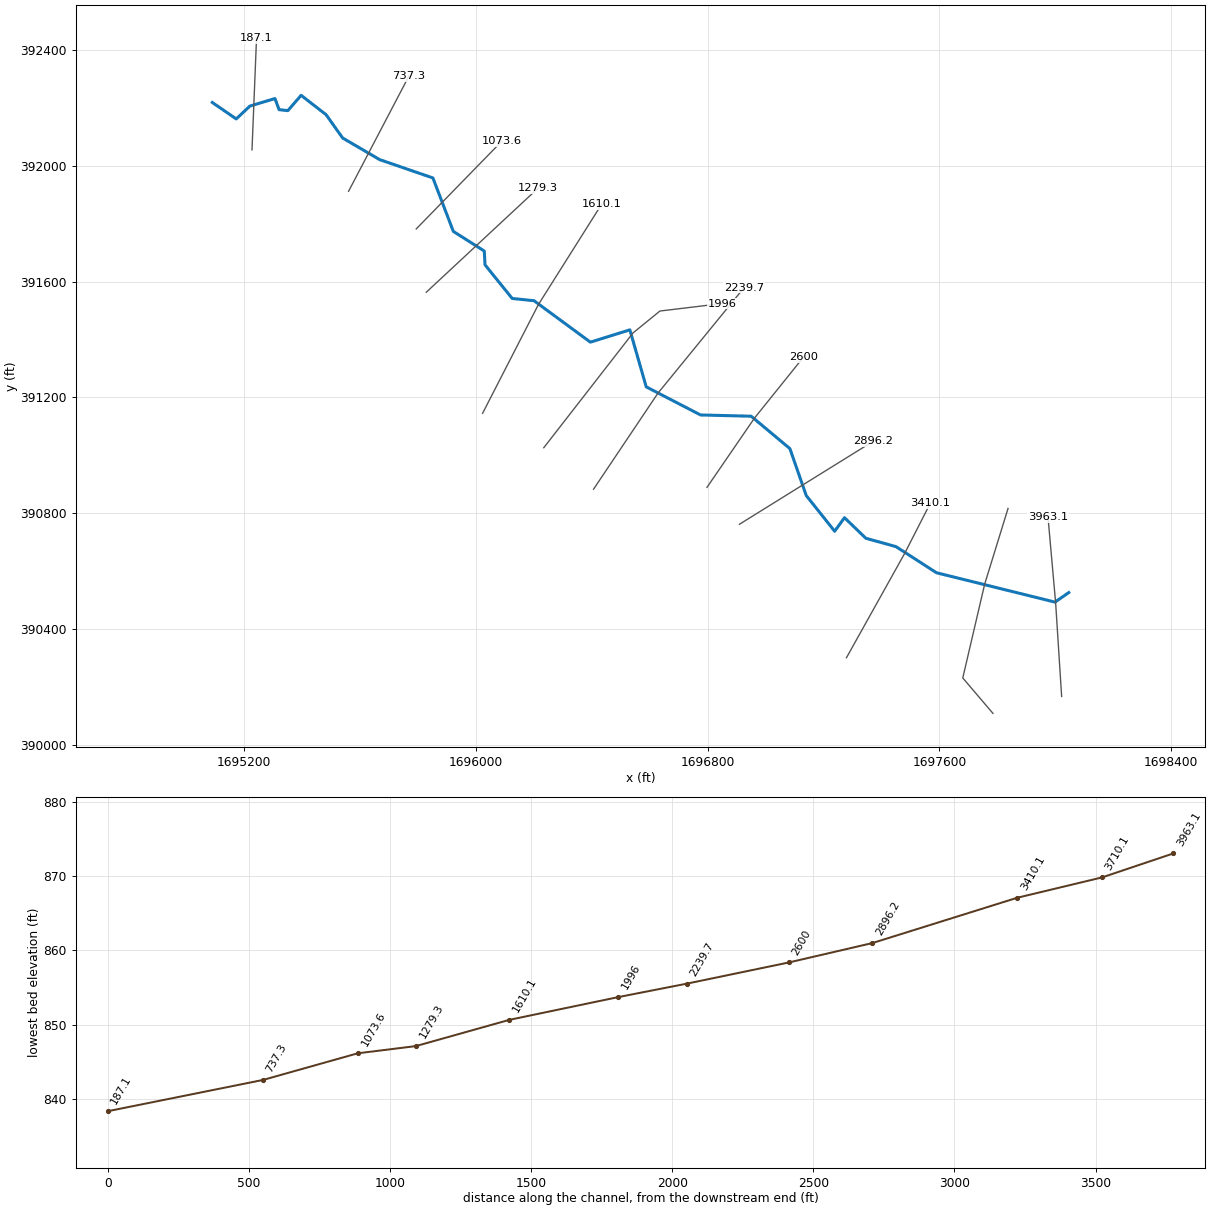
--- BALLARDFK.prj (project) ---

Proj Title=BALLARDFK
Current Plan=p01
Default Exp/Contr=0,0
English Units
Geom File=g01
Flow File=f01
Plan File=p01
BEGIN DESCRIPTION:
END DESCRIPTION:
DSS Export Rating Curves= 0
DSS Export Rating Curve Sorted= 0
DSS Export Volume Flow Curves= 0
DXF OffsetX= 0
DXF OffsetY= 0
DXF ScaleX= 0
DXF ScaleY= 0

--- BALLARDFK.p01 (plan) ---

Plan Title=Floodplain
Program Version=4.00
Geom File=g01
Flow File=f01
K Sum by GR=0
Std Step Tol=0.01
Critical Tol=0.01
Num of Std Step Trials=20
Max Error Tol=0.3
Flow Tol Ratio=0.001
Split Flow NTrial=30
Split Flow Tol=0.02
Split Flow Ratio=0.02
Log Output Level=0
Friction Slope Method=1
Unsteady Friction Slope Method=2
Unsteady Bridges Friction Slope Method=1
Global Log Level=0
CheckData=False
Run HTab=0
Run UNet=0
Run PostProcess=0
UNET Theta=0
UNET Theta Warmup=0
UNET ZTol=0
UNET ZSATol=0
UNET MxIter=0
UNET MaxInSteps=0
UNET DtIC=0
UNET DtMin=0
UNET MaxCRTS=0
UNET WFStab=0
UNET SFStab=0
UNET WFX=0
UNET SFX=0
UNET DSS MLevel=0
UNET DZMax Abort=0
UNET Convert EG Bridges=0
UNET Use Existing IB Tables=0
UNET Froude Limit=0
UNET Froude Power=0
Write IC File=0
Echo Input=False
Echo Output=False
Write Detailed=0

--- BALLARDFK.f01 (steady flow) ---

Flow Title=NFF Regression Equation
Program Version=4.10
Number of Profiles= 1
Profile Names=P100yr
River Rch & RM=BALLARDFK,Main            ,3963.1
903.3814
River Rch & RM=BALLARDFK,Main            ,1610.1
994.2503
River Rch & RM=BALLARDFK,Main            ,187.1
1018.628
Boundary for River Rch & Prof#=BALLARDFK,Main            , 1
Up Type= 0
Dn Type= 3
Dn Slope=0.007701
DSS Import GetInterval= 0
DSS Import GetPeak= 0
DSS Import FillOption= 0

--- BALLARDFK.g01 (geometry) ---

Geom Title=USGS 10m DEM
Program Version=4.10

River Reach=BALLARDFK       ,Main
Reach XY= 30
     1698046.696      390525.567     1697998.953       390492.58
     1697589.925      390594.143     1697450.168      390684.421
     1697346.348       390713.24     1697272.564      390784.421
     1697238.709      390737.546     1697140.619       390860.81
     1697084.196      391023.136     1696950.515      391135.115
     1696775.776      391139.456     1696588.276      391236.678
     1696531.852      391433.639     1696395.567      391391.105
      1696201.21      391534.334     1696125.689      391542.147
     1696031.939      391658.466     1696029.335      391706.209
     1695922.564      391773.917     1695852.078      391958.726
     1695668.457      392021.998     1695540.619      392096.747
     1695483.328      392177.476     1695397.184      392244.328
     1695351.383      392191.365     1695321.001      392194.837
     1695306.926      392233.199     1695220.133       392206.99
     1695173.258      392162.719     1695090.716      392219.581

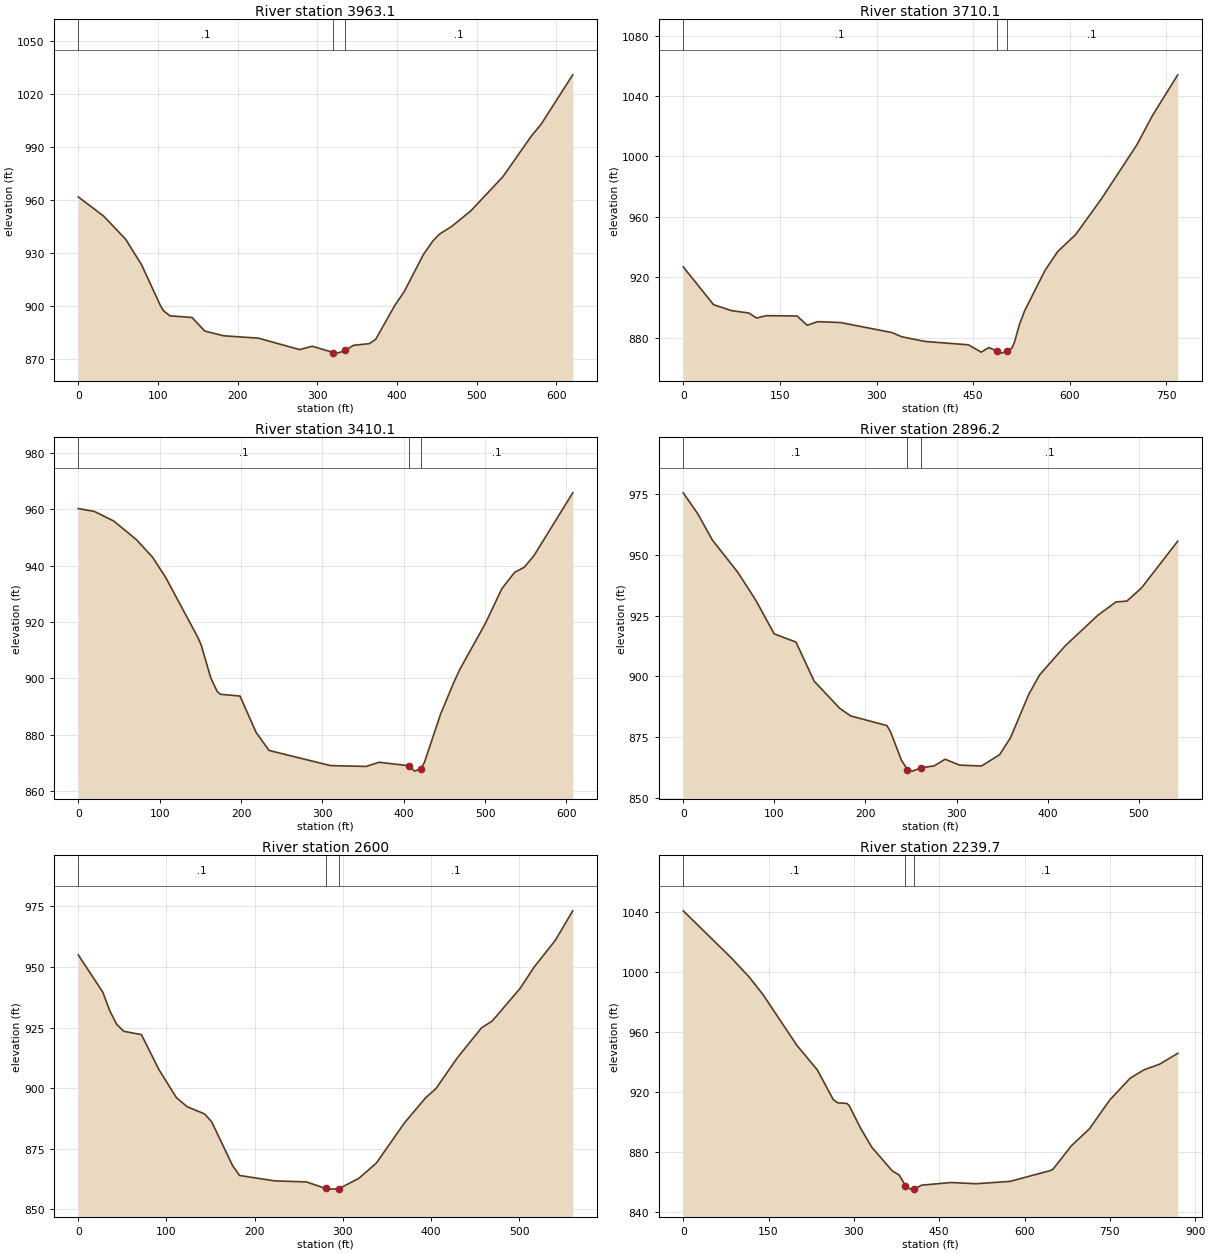
Type RM Length L Ch R = 1 ,3963.1  ,259.8,253,244.1
XS GIS Cut Line= 3
     1698022.116      390166.384     1698001.283      390491.037
     1697975.098      390785.057
#Sta/Elev= 30
       0  961.57    31.7  950.76    59.5  937.56    79.4  923.17   103.2  899.93
   107.1  897.05     115  894.22   142.8  893.28   158.7  885.61   182.5  882.92
   226.1  881.58   277.7  875.09   293.6  877.01   320.1  873.44   325.3   873.1
   335.1  874.64   345.3  877.52   365.2  878.47   373.2   880.9   397.1  900.04
   409.1  908.01     433  928.86     445  936.62     453   940.4   468.9  944.94
   492.9   953.8   532.8  972.99   568.6  996.04   580.6 1002.56   620.5 1030.69
#Mann= 3 , 0 , 0
       0      .1       0   320.1    .045       0   335.1      .1       0
Bank Sta=320.1,335.1
XS Rating Curve= 0 ,0
Exp/Cntr=0.3,0.1

Type RM Length L Ch R = 1 ,3710.1  ,306.3,300,296.1
XS GIS Cut Line= 4
     1697784.994      390107.973     1697680.828      390230.369
     1697756.571      390555.124     1697837.078      390816.307
#Sta/Elev= 30
       0  926.95      47  901.94    74.5  898.02   101.9  896.39   113.7  893.11
   129.4  894.68   176.6  894.42   192.5  888.28   208.4  890.69   244.1   890.1
   323.5  883.51   339.4  880.65   375.1   877.6   442.6  875.36   462.4  870.52
   474.3  873.55   486.7  871.27   494.2  869.86   501.7  871.41     510  873.07
     514  877.03   521.9  888.94   529.8  897.84   561.5  924.62   581.3  937.14
   609.1  948.38   648.7  971.75   704.1 1007.73   727.9 1026.87   767.5 1054.05
#Mann= 3 , 0 , 0
       0      .1       0   486.7    .045       0   501.7      .1       0
Bank Sta=486.7,501.7
XS Rating Curve= 0 ,0
Exp/Cntr=0.3,0.1

Type RM Length L Ch R = 1 ,3410.1  ,512.3,513.9,488.3
XS GIS Cut Line= 3
     1697279.388      390300.283     1697480.595      390661.406
     1697568.848      390834.536
#Sta/Elev= 30
       0  960.24    19.9  959.22    43.7   955.8    71.6  949.19    91.4  942.94
   107.3  935.89   147.1  914.48     151   911.9     163  900.04   170.9  895.29
   174.9  894.37   198.8  893.74   218.6  880.83   234.5  874.45     310  869.08
   353.8  868.78   369.7  870.27   405.9  869.04   413.4  867.12   420.9  868.02
   425.3  870.12   445.1  887.21     461  898.24   468.9   903.2   500.6  919.65
   520.5   931.8   536.3  937.62   548.2  939.44   560.1  943.57   607.7  965.82
#Mann= 3 , 0 , 0
       0      .1       0   405.9    .045       0   420.9      .1       0
Bank Sta=405.9,420.9
XS Rating Curve= 0 ,0
Exp/Cntr=0.3,0.1

Type RM Length L Ch R = 1 ,2896.2  ,285.9,296.2,303.8
XS GIS Cut Line= 3
     1696909.994      390761.619     1697123.536      390894.432
     1697370.932      391048.078
#Sta/Elev= 30
       0  975.67      16  966.98    31.9  956.25    59.9   942.9    79.8   931.3
    99.8  917.56   123.7  914.17   143.7  898.05   171.6  886.92   183.6  883.76
   223.5  879.76   227.5  877.19   239.5  865.46     246  861.64   251.5     861
     261  862.35   275.4  863.17   287.4   865.9   303.3  863.47   327.3  863.12
   347.2  867.77   359.2   874.8   379.1  892.56   391.1  900.66     419  912.56
   454.9  925.18   474.9  930.72   486.8  931.05   502.8  936.43   542.7  955.76
#Mann= 3 , 0 , 0
       0      .1       0     246    .045       0     261      .1       0
Bank Sta=246,261
XS Rating Curve= 0 ,0
Exp/Cntr=0.3,0.1

Type RM Length L Ch R = 1 ,2600    ,360.1,360.3,359.3
XS GIS Cut Line= 3
     1696798.015      390889.223     1696962.078      391128.807
     1697131.348      391339.744
#Sta/Elev= 30
       0     955    27.8  939.63    35.8  931.87    43.8  926.23    51.7  923.47
    71.6   922.1    91.5  907.64   111.4  896.07   123.3   892.4   143.2   889.4
   151.2  886.22     175  868.09     183  864.01   222.8  861.78   258.6  861.36
   280.5  858.68   286.4  858.38   295.5  858.54   318.2  862.83   338.1  869.13
   369.9  885.68   393.8     896   405.7  899.86   429.6  912.39   457.4  924.93
   469.4  927.67   501.2  941.21   517.1     950   540.9  960.92   560.8  973.15
#Mann= 3 , 0 , 0
       0      .1       0   280.5    .045       0   295.5      .1       0
Bank Sta=280.5,295.5
XS Rating Curve= 0 ,0
Exp/Cntr=0.3,0.1

Type RM Length L Ch R = 1 ,2239.7  ,245.2,243.7,239
XS GIS Cut Line= 3
     1696406.483      390882.852     1696628.744      391214.744
     1696925.633       391579.02
#Sta/Elev= 30
       0 1040.87    83.9 1009.75   115.8  996.81   139.8  985.32   199.7  951.32
   235.7  934.94   263.6  915.24   271.6  912.98   287.6  912.62   291.6  911.22
   311.6  896.24   331.5  883.42   367.5  867.68   379.5  864.96   390.6  857.91
   399.4  855.53   405.6  855.68   419.4  858.18   471.1  859.94   514.9  859.12
   574.7  860.69   646.4  867.99   650.3  868.88   682.2  884.34   714.1  895.68
   749.9  914.91   785.7  929.39   809.6  934.91   837.5  938.75   869.4  945.96
#Mann= 3 , 0 , 0
       0      .1       0   390.6    .045       0   405.6      .1       0
Bank Sta=390.6,405.6
XS Rating Curve= 0 ,0
Exp/Cntr=0.3,0.1

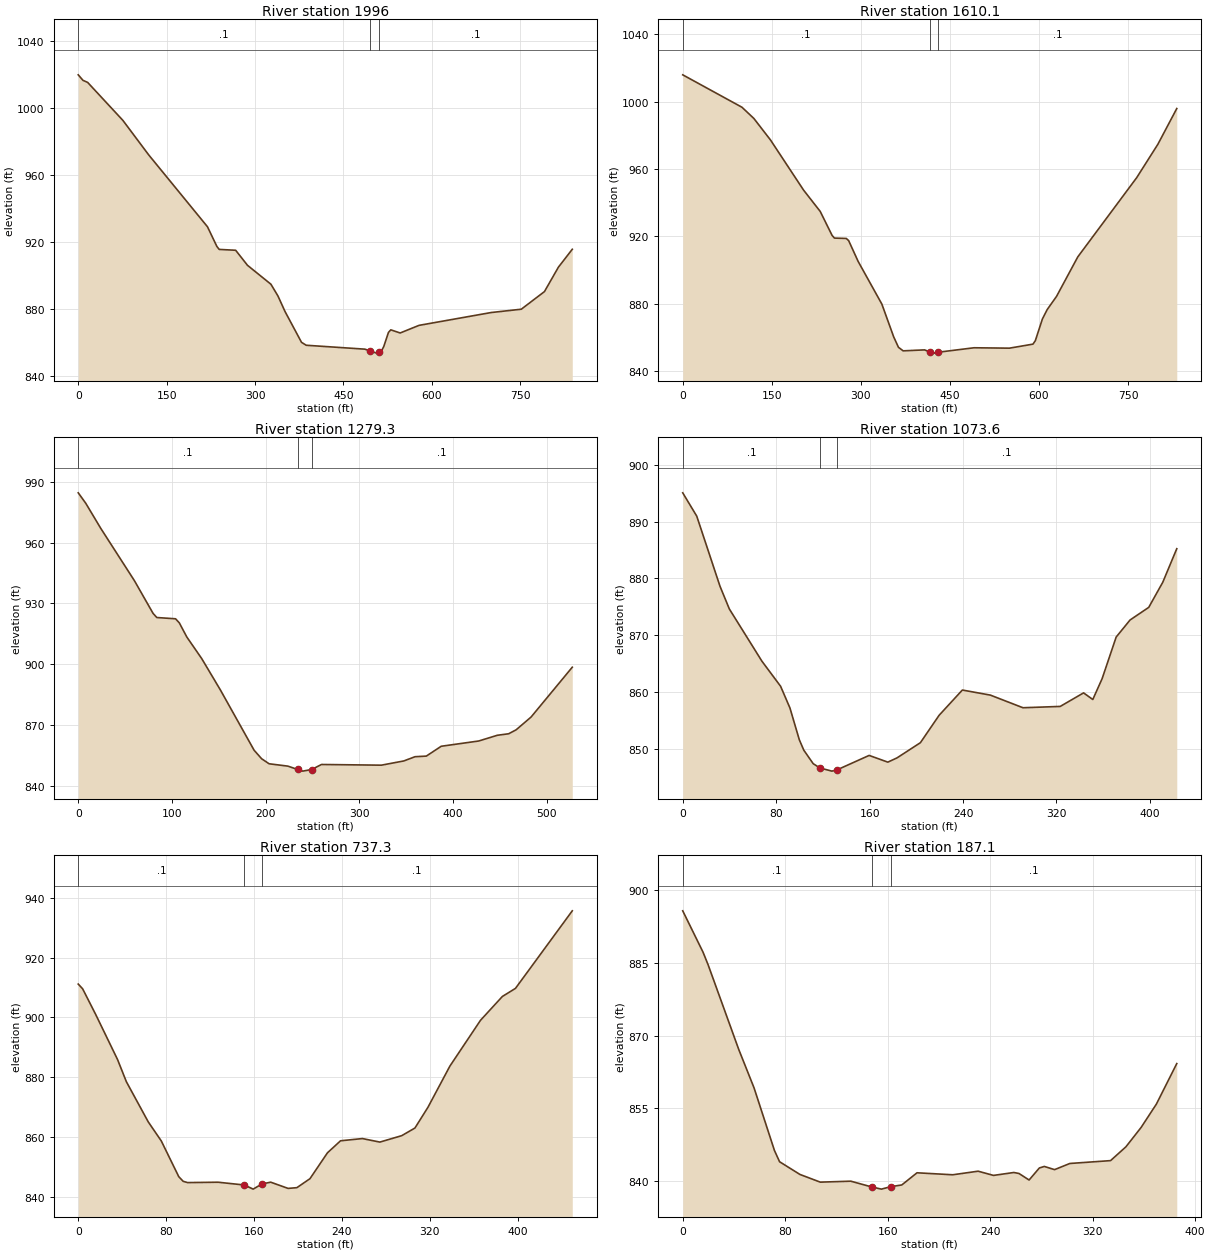
Type RM Length L Ch R = 1 ,1996    ,379.1,385.9,394.8
XS GIS Cut Line= 4
     1696234.749      391026.237     1696542.807      391423.078
     1696635.528      391498.681     1696850.098       391524.64
#Sta/Elev= 30
       0 1019.89       8 1016.61      16 1015.36    75.8  992.66   119.6  972.06
   219.3  929.15   235.2  917.42   239.2  915.64   267.1  915.13   287.1  906.17
   326.9  894.85   338.9   887.8   350.9  878.51   378.8  860.16   386.8  858.41
   486.4  856.08   495.3  854.98   506.4  853.71   510.3  854.11   514.3  854.91
   518.3   857.6   526.3  866.06   530.3  867.62   546.2  865.74   578.2  870.29
   700.6  877.95   751.7  879.93     791  890.46   814.6  904.99   838.2  915.72
#Mann= 3 , 0 , 0
       0      .1       0   495.3    .045       0   510.3      .1       0
Bank Sta=495.3,510.3
XS Rating Curve= 0 ,0
Exp/Cntr=0.3,0.1

Type RM Length L Ch R = 1 ,1610.1  ,337.5,330.9,325.7
XS GIS Cut Line= 3
     1696023.582      391145.205     1696216.566       391521.77
     1696434.375       391867.76
#Sta/Elev= 30
       0 1015.93    99.8  996.66   119.8  990.01   147.7  977.28   203.6  947.41
   231.5  934.82   251.5  920.58   255.5  918.96   275.4  918.75   279.4  917.48
   295.4  905.11   335.3  879.78   355.3  860.26   363.3  854.09   371.2  851.99
   407.2  852.57   415.6  851.43   423.1  850.64   430.6   851.2   490.6  853.82
   550.2  853.59   589.8  855.98   593.8  858.04   605.7  870.92   613.7  876.46
   629.5  884.34   665.3   907.8   764.5  954.85   800.2   974.7     832  995.91
#Mann= 3 , 0 , 0
       0      .1       0   415.6    .045       0   430.6      .1       0
Bank Sta=415.6,430.6
XS Rating Curve= 0 ,0
Exp/Cntr=0.3,0.1

Type RM Length L Ch R = 1 ,1279.3  ,204.8,205.7,206.3
XS GIS Cut Line= 2
     1695829.265      391563.703     1696214.682      391923.078
#Sta/Elev= 30
       0  984.55       8  979.41      24  967.02    59.9  941.18    79.8  925.03
    83.8  922.96   103.8  922.34   107.8  920.34   115.8  913.36   131.7  902.69
   151.7  887.14   187.6  857.42   195.6  853.22   203.6  850.73   223.6  849.57
   233.9  847.94   239.5   847.1   248.9  847.89   259.5  850.38   323.4  850.04
   347.3  852.13   359.3  854.22   371.3  854.52   387.2  859.38   427.2  861.98
   447.1  864.81   459.1  865.55   467.1   867.5     483  873.79     527  898.42
#Mann= 3 , 0 , 0
       0      .1       0   233.9    .045       0   248.9      .1       0
Bank Sta=233.9,248.9
XS Rating Curve= 0 ,0
Exp/Cntr=0.3,0.1

Type RM Length L Ch R = 1 ,1073.6  ,327.3,336.3,343.6
XS GIS Cut Line= 2
     1695794.499      391782.482     1696089.638      392085.433
#Sta/Elev= 30
       0  895.04      12  890.94    31.9  878.62    39.9  874.63    67.8  865.45
    83.8  861.04    91.8  857.22    99.8  851.65   103.7   849.8   111.7  847.44
   117.4  846.69   127.7  846.13   132.4  846.38   159.6  848.89   175.6  847.71
   183.5  848.46   203.5  851.13   219.5  855.94   239.4  860.38   263.4  859.49
   291.3  857.27   323.2   857.5   343.2  859.88   351.1  858.72   359.1  862.39
   371.1  869.69     383  872.69     399  874.91     411  879.32     423  885.22
#Mann= 3 , 0 , 0
       0      .1       0   117.4    .045       0   132.4      .1       0
Bank Sta=117.4,132.4
XS Rating Curve= 0 ,0
Exp/Cntr=0.3,0.1

Type RM Length L Ch R = 1 ,737.3   ,501.9,550.2,562
XS GIS Cut Line= 2
     1695561.036      391912.661     1695769.369      392311.098
#Sta/Elev= 30
       0  911.14       4  909.56    15.9  900.96    35.8  885.87    43.8  878.47
    63.7  865.04    75.6  858.64    91.5  846.69    95.5  845.14    99.5  844.72
   127.3  844.84   151.2  843.91   159.2  842.53   167.1  844.24   175.1  844.86
     191  842.77     199  843.02   210.9  846.03   226.8  854.68   238.7   858.7
   258.6  859.45   274.5  858.27   294.4  860.42   306.4  862.97   318.3  869.94
   338.2  883.68   366.1  899.03     386     907   397.9   909.7   449.6  935.65
#Mann= 3 , 0 , 0
       0      .1       0   151.2    .045       0   167.1      .1       0
Bank Sta=151.2,167.1
XS Rating Curve= 0 ,0
Exp/Cntr=0.3,0.1

Type RM Length L Ch R = 1 ,187.1   ,196.6,187.1,177.3
XS GIS Cut Line= 2
     1695227.703       392055.89     1695243.328      392441.307
#Sta/Elev= 30
       0  895.72    15.9  887.16    19.9  884.53    43.7  867.14    55.7  859.18
    71.6  846.28    75.6  843.96    91.5  841.34   107.4  839.75   131.2  839.95
   147.5  838.76   155.1  838.31   162.5  838.82     171  839.17   182.9  841.68
   210.8  841.27   230.6  842.01   242.6  841.14   258.5  841.74   262.5  841.54
   270.4  840.19   278.4  842.67   282.3  842.99   290.3  842.33   302.2   843.6
     334  844.19     346  847.04   357.9  851.05   369.8  855.86   385.7  864.21
#Mann= 3 , 0 , 0
       0      .1       0   147.5    .045       0   162.5      .1       0
Bank Sta=147.5,162.5
XS Rating Curve= 0 ,0
Exp/Cntr=0.3,0.1

Chan Stop Cuts=-1
Use User Specified Reach Order=0
Composite Channel Slope=5